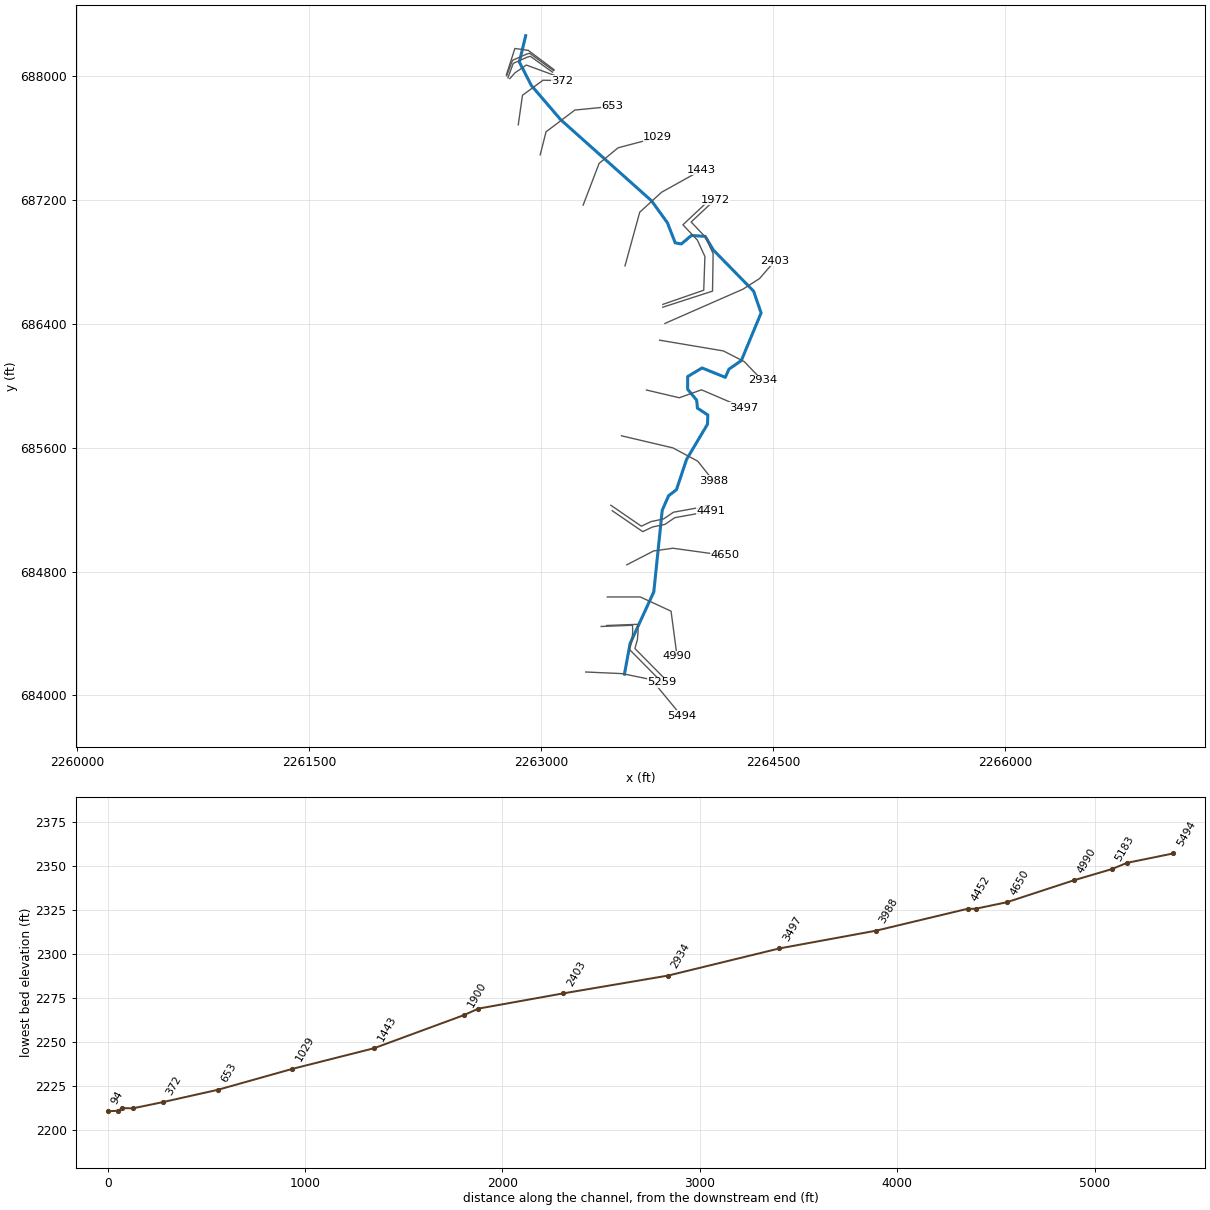
--- LAURELRN2.prj (project) ---

Proj Title=LAURELRN2
Current Plan=p01
Default Exp/Contr=0,0
English Units
Geom File=g01
Flow File=f01
Plan File=p01
BEGIN DESCRIPTION:
----------MODEL BY WOOD PLC 2022----------
AFH study
Randolph County, WV
HEC-RAS Version: RAS 6.2
Vertical Datum: NAVD88
Projection: NAD 1983 StatePlane West Virginia S FIPS 4702 (US Feet)
Terrain: 1-meter LIDAR (FEMA Region III 3DEP collected 2016-2018)
Land Use: 2019 NLCD
Hydrologic Method:
WV SIR2010-5033 regression equations
Additional Model Notes:
None
END DESCRIPTION:
DSS Export Rating Curves= 0
DSS Export Rating Curve Sorted= 0
DSS Export Volume Flow Curves= 0
DXF OffsetX= 0
DXF OffsetY= 0
DXF ScaleX= 0
DXF ScaleY= 0

--- LAURELRN2.p01 (plan) ---

Plan Title=Floodplain
Program Version=6.20
Short Identifier=Floodplain
Geom File=g01
Flow File=f01
Subcritical Flow
K Sum by GR= 0
Std Step Tol= 0.01
Critical Tol= 0.01
Num of Std Step Trials= 20
Max Error Tol= 0.3
Flow Tol Ratio= 0.001
Split Flow NTrial= 30
Split Flow Tol= 0.02
Split Flow Ratio= 0.02
Log Output Level= 0
Friction Slope Method= 1
Unsteady Friction Slope Method= 2
Unsteady Bridges Friction Slope Method= 1
Parabolic Critical Depth
Global Vel Dist= 0 , 0 , 0
Global Log Level= 0
CheckData=True
Encroach Param=-1 ,0,0, 0
Mapping Interval=1HOUR
Computation Time Step Use Courant=        0
Computation Time Step Use Time Series=    0
Computation Time Step Count To Double=0
Computation Time Step Max Doubling=0
Computation Time Step Max Halving=0
Computation Time Step Residence Courant=0
Run HTab= 0
Run UNet= 0
Run Sediment= 0
Run PostProcess= 0
Run WQNet= 0
Run RASMapper=-1
UNET Theta= 0
UNET Theta Warmup= 0
UNET ZTol= 0
UNET ZSATol= 0
UNET MxIter= 0
UNET Max Iter WO Improvement= 0
UNET MaxInSteps= 0
UNET DtIC= 0
UNET DtMin= 0
UNET MaxCRTS= 0
UNET WFStab= 0
UNET SFStab= 0
UNET WFX= 1
UNET SFX= 1
UNET Gravity=32.174
UNET 1D Methodology=Finite Difference
UNET DSS MLevel= 1
UNET Pardiso=0
UNET DZMax Abort= 0
UNET Use Existing IB Tables= 0
UNET Froude Reduction=False
UNET Froude Limit= 0
UNET Froude Power= 0
UNET D1 Cores= 0
UNET WindReference=Eulerian
UNET WindDragFormulation=Hsu (1988)
UNET D2 Coriolis=0
UNET D2 Cores= 0
UNET D2 Theta= 1
UNET D2 Theta Warmup= 1
UNET D2 Z Tol= 0.01
UNET D2 Volume Tol= 0.01
UNET D2 Max Iterations= 20
UNET D2 Equation= 0
UNET D2 RampUpFraction=0.1
UNET D2 TimeSlices= 1
UNET D2 Turbulence Formulation=Non-Conservative (original)
UNET D2 Eddy Viscosity=0.3
UNET D2 Transverse Eddy Viscosity=0.1
UNET D2 Smagorinsky Mixing=0
UNET D2 BCVolumeCheck=0
UNET D2 Cores=0
UNET D2 SolverType=PARDISO (Direct)
UNET D2 Minimum Iterations= 2147483647
UNET D2 Maximum Iterations= 2147483647
UNET D2 Restart Number= 10
UNET D2 Relaxation Coeff=1.3
UNET D2 SOR Precondition Iterations= 10
UNET D2 ILUT Maximum Fill= 8
UNET D2 ILUT Tolerance=1E-08
UNET D1D2 MaxIter= 0
UNET D1D2 ZTol=0.01
UNET D1D2 QTol=0.1
UNET D1D2 MinQTol=1
Write IC File= 0
Write IC File at Fixed DateTime=0
Write IC File at Sim End=0
Echo Input=False
Echo Parameters=False
Echo Output=False
Write Detailed= 0
HDF Write Warmup=0
HDF Write Time Slices=0
HDF Flush=0
HDF Compression= 1
HDF Chunk Size= 1
HDF Spatial Parts= 1
HDF Use Max Rows=0
HDF Fixed Rows= 1
Calibration Method= 0
Calibration Iterations= 20
Calibration Max Change=0.05
Calibration Tolerance=0.2
Calibration Maximum=1.5
Calibration Minimum=0.5
Calibration Optimization Method= 1
WQ AD Non Conservative
WQ ULTIMATE=-1
WQ Max Comp Step=1HOUR
WQ Output Interval=15MIN
WQ Output Selected Increments= 0
WQ Output face flow=0
WQ Output face velocity=0
WQ Output face area=0
WQ Output face dispersion=0
WQ Output cell volume=0
WQ Output cell surface area=0
WQ Output cell continuity=0
WQ Output cumulative cell continuity=0
WQ Output face conc=0
WQ Output face dconc_dx=0
WQ Output face courant=0
WQ Output face peclet=0
WQ Output face adv mass=0
WQ Output face disp mass=0
WQ Output cell mass=0
WQ Output cell source sink temp=0
WQ Output nsm pathways=0
WQ Output nsm derived pathways=0
WQ Create Restart=0
WQ Fixed Restart=0
WQ System Summary=0
WQ Write To DSS=0
Sorting and Armoring Iterations= 10
XS Update Threshold= 0.02
Bed Roughness Predictor= 0
Hydraulics Update Threshold= 0.02
Energy Slope Method= 1
Volume Change Method= 1
Sediment Retention Method= 0
Sediment TS Multiplier= 1
Warm Up Method= 0
XS Weighting Method= 0
Number of US Weighted Cross Sections= 1
Number of DS Weighted Cross Sections= 1
Upstream XS Weight=0
Main XS Weight=1
Downstream XS Weight=0
Number of DS XS's Weighted with US Boundary= 1
Upstream Boundary Weight= 1
Weight of XSs Associated with US Boundary= 0
Number of US XS's Weighted with DS Boundary= 1
Downstream Boundary Weight= 0.5
Weight of XSs Associated with DS Boundary= 0.5
Percentile Method= 0
Sediment Output Level= 3
Mass or Volume Output= 0
Output Increment Type= 1
Profile and TS Output Increment= 1
Transport Output Increment 1
XS Output Flag= 0
XS Output Increment= 10
Read HDF5 Sediment Hotstart= 0
Sediment Hotstart Type= 0
Write Gradation File= 0
Read Gradation Hotstart= 0
Write HDF5 File= 1
Write Binary Output= 1
Write DSS Sediment File= 0
DSS Sediment Output Type= 1
SV Curve= 0
Specific Gage Flag= 0
Subcell Erosion Methods= 0
Subcell Deposition Methods= 0
Advection Scheme= 1
Matrix Solver= 0
Implicit Weighting Factor= 1
Maximum Outer Loop Convergence Iterations= 5
Convergence Maximum Absolute= 0.001
Convergence RMSE= 0.0001
Grain Fractions Max Abs Error= 0.001
Max Subgrid Regions= 1
Max Subgrid Length Scale= 3.402823E+38
Initial Layer Thickness= 3.402823E+38
Min Layer Thickness= 3.402823E+38
Max Layer Thickness= 3.402823E+38
Number of Layers= 5

--- LAURELRN2.f01 (steady flow) ---

Flow Title=Flow
Program Version=6.20
Number of Profiles= 1
Profile Names=P100yr
River Rch & RM=LAURELRN2,Main            ,5494
     727
River Rch & RM=LAURELRN2,Main            ,4650
     573
Boundary for River Rch & Prof#=LAURELRN2,Main            , 1
Up Type= 0
Dn Type= 3
Dn Slope=0.01847
DSS Import GetInterval= 0
DSS Import GetPeak= 0
DSS Import FillOption= 0

--- LAURELRN2.g01 (geometry) ---

Geom Title=Geometry
Program Version=6.20

River Reach=LAURELRN2       ,Main
Reach XY= 30
2263539.03500001684137.735000014 2263575.2643754684334.996946459
2263728.64900002684668.9850000142263783.25200002685196.996000022
2263824.50699998685290.480000019     2263875.309685329.945000008
2263940.42399998685525.2349999992264075.80200002685752.802000001
2264077.72500001685812.3390000162264010.60141468685856.642265311
2264005.65743571685907.879865548     2263947.501685978.452999994
2263947.64900005686060.6350000052264040.55100004686116.253000021
     2264190.928 686055.392000022264213.93600002686108.181000009
2264294.09201307   686163.6448592264422.00956203686471.521794583
2264373.57700005686612.2260000112264114.12600002686877.401000008
2264060.93800002686966.2280000152263971.79100001686972.254000008
     2263906.749686917.630999997     2263866.976686924.596000016
2263817.10299999687053.3740000132263714.61234932687195.754783857
2263127.77700002687719.5380000172262937.40900002 687941.40200001
2262859.81726129688092.9388693722262900.84302241688262.970971376

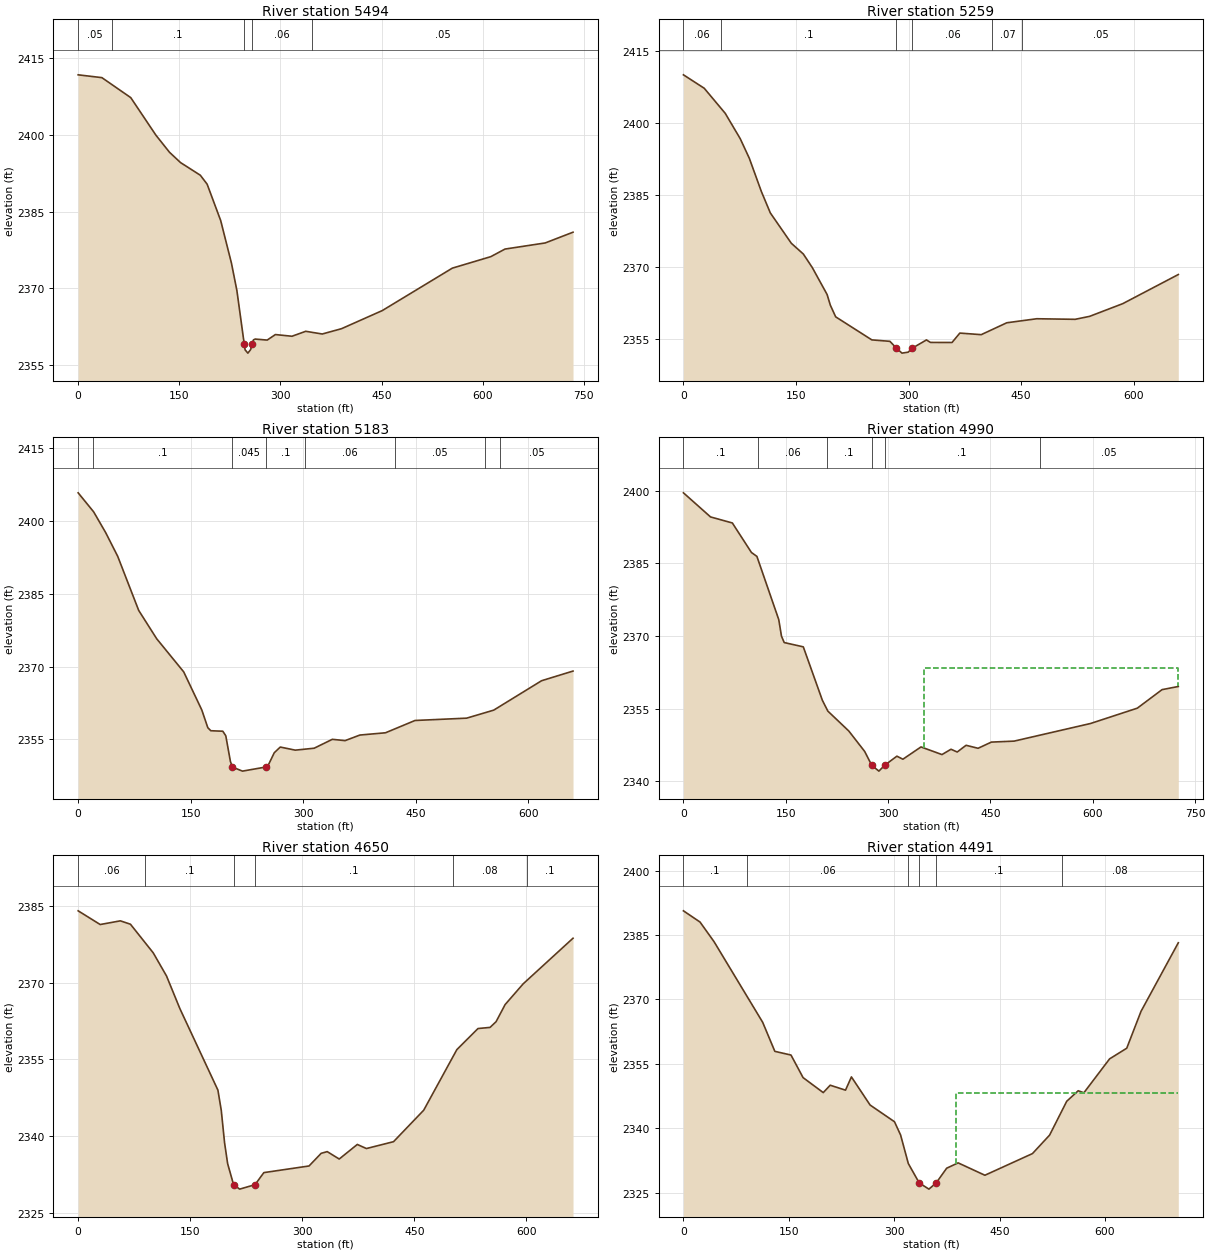
Type RM Length L Ch R = 1 ,5494    ,241.1,235.7,219.5
XS GIS Cut Line= 4
2263289.01763394684151.4221623432263525.80071689684140.876162176
2263714.46824756684101.7415429032263908.17441712683867.174366058
#Sta/Elev= 30
       0 2411.78    35.2 2411.23      78 2407.32   115.3 2399.98   135.5 2396.63
   151.8 2394.62   181.2 2392.14   191.3 2390.39   211.4 2383.27   227.3 2374.97
   235.4  2369.6  246.282359.145   247.6 2357.99   251.7 2357.35   255.8 2358.04
   258.22359.145   259.9 2359.93   262.5  2360.1   280.3  2359.9   292.5 2360.98
   317.1 2360.65   337.5 2361.62     362 2361.09   390.6 2362.13     451 2365.67
   554.9 2373.97     612 2376.22     633  2377.7   692.7  2378.9   733.9    2381
#Mann= 5, -1 ,  0
       0    0.05       0      50     0.1       0  246.28   0.045       0
   258.2    0.06       0  347.02    0.05       0
Bank Sta=246.28,258.2
XS Rating Curve= 0 ,0
Exp/Cntr=0.3,0.1

Type RM Length L Ch R = 1 ,5259    ,92.2,75.2,72.9
XS GIS Cut Line= 6
2263388.48381966684445.624756359 2263591.2745798684453.363946751
2263592.06287493684407.2486813282263587.72725169684354.432907255
2263571.56720141684296.8873623682263780.80258272 684085.17631862
#Sta/Elev= 30
       0 2410.01    27.7 2407.21    55.7 2401.98    75.7 2396.69    87.8 2392.61
   103.8  2385.7   115.8 2381.21   143.8 2374.88   159.8 2372.64   171.8  2369.8
   191.5 2364.19   195.8 2361.97   202.9 2359.54   251.1 2354.73   275.2 2354.43
  283.812353.022   291.3 2351.97   299.5 2352.17   305.2 2353.02   323.9 2354.72
   329.3  2354.2     358 2354.19   368.4 2356.15   396.9 2355.82     431  2358.3
   470.9 2359.14   522.1 2359.02   541.4 2359.64   585.6 2362.29   659.6 2368.36
#Mann= 6, -1 ,  0
       0    0.06       0      50     0.1       0  283.81   0.045       0
   305.2    0.06       0  411.89    0.07       0  451.89    0.05       0
Bank Sta=283.81,305.2
XS Rating Curve= 0 ,0
Exp/Cntr(USF)=0,0
Exp/Cntr=0.3,0.1

Type RM Length L Ch R = 1 ,5183    ,169.2,193,210.3
XS GIS Cut Line= 6
2263423.53035148684451.8904163472263626.32111162684459.629606739
2263627.10940676684413.5143413162263622.77378352684360.698567242
2263606.61373324684303.1530223562263815.84911455684091.441978608
#Sta/Elev= 30
       0 2405.79    20.7 2401.86    36.7 2397.59    52.7 2392.72    80.7 2381.57
   104.7 2375.73   140.7 2368.91   164.8 2361.07   172.8 2357.42   176.8 2356.79
   192.8 2356.69   196.8 2355.74   202.9 2350.49   205.52349.321     219 2348.47
  250.342349.321   253.4  2349.7   261.4 2352.26   269.4 2353.43   289.4 2352.79
   314.6 2353.19   338.8 2355.02   355.8 2354.75   375.5  2355.9   409.7 2356.37
     449  2358.9   517.8 2359.38   553.9 2361.03   617.7 2367.09   659.6 2369.08
#Mann= 8, -1 ,  0
       0    0.06       0      20     0.1       0   205.5   0.045       0
  250.34     0.1       0  301.87    0.06       0  421.89    0.05       0
  541.89    0.06       0  561.89    0.05       0
Bank Sta=205.5,250.34
XS Rating Curve= 0 ,0
Exp/Cntr(USF)=0,0
Exp/Cntr=0.3,0.1

Type RM Length L Ch R = 1 ,4990    ,335.3,339.9,348.3
XS GIS Cut Line= 4
2263428.46993009684636.3658196332263641.63121587684636.342133466
2263840.18190228684544.4467973122263878.88926772684253.580914379
#Sta/Elev= 30
       0 2399.59    39.7 2394.61    71.7 2393.36    99.7 2387.26   107.7 2386.45
   139.7  2373.4   143.7 2369.98   147.7 2368.65   175.7 2367.76   203.7  2356.7
   211.7 2354.48   242.4 2350.37   265.7 2346.14  276.022343.285   286.5 2342.08
  294.942343.285   312.9 2345.17   321.7 2344.54   348.2 2347.08     379  2345.5
   392.2  2346.6   401.3 2346.03   414.3 2347.42   431.9  2346.8   451.4 2348.08
   484.7 2348.28   596.7 2351.92   665.3 2355.09   701.6 2358.92   725.4 2359.57
#Mann= 6, -1 ,  0
       0     0.1       0     110    0.06       0     210     0.1       0
  276.02   0.045       0  294.94     0.1       0  521.95    0.05       0
#XS Ineff= 2 , 0
                          352.35         2363.34
Permanent Ineff=
       F       F
Bank Sta=276.02,294.94
XS Rating Curve= 0 ,0
Exp/Cntr=0.3,0.1

Type RM Length L Ch R = 1 ,4650    ,157.9,159.2,158.2
XS GIS Cut Line= 4
 2263553.9850815684843.9040131352263727.87515719684933.782449841
2263852.40048215 684951.179370242264190.25747032684904.483959801
#Sta/Elev= 30
       0 2384.04    29.5 2381.36    56.5 2382.08      70 2381.42   100.5 2375.82
   118.3 2371.29   136.2  2364.9   187.1 2348.96   191.6 2344.99     196 2338.68
   200.1 2334.58  208.082330.461   216.2 2329.59  236.782330.461   248.6 2332.82
   309.1 2334.12   325.3 2336.59   333.4 2336.93   349.5 2335.48   373.7 2338.33
   385.9 2337.53   422.2 2338.87   462.6 2345.03     507 2356.89   535.3 2361.01
   551.4 2361.23   559.5 2362.35   571.6  2365.7   595.8 2369.76   662.5 2378.68
#Mann= 6, -1 ,  0
       0    0.06       0      90     0.1       0  208.08   0.045       0
  236.78     0.1       0  501.48    0.08       0  601.48     0.1       0
Bank Sta=208.08,236.78
XS Rating Curve= 0 ,0
Exp/Cntr(USF)=0,0
Exp/Cntr=0.3,0.1

Type RM Length L Ch R = 1 ,4491    ,36.4,39.6,40.5
XS GIS Cut Line= 6
2263459.96365222685193.7888955522263657.05216994685058.495873287
2263720.70539972685088.5102086822263800.76315828685105.339260602
2263864.63741242685148.7840974252264096.46480059685190.594918371
#Sta/Elev= 30
       0 2390.62    23.6 2388.01    43.5 2383.46   112.8 2364.68   130.1 2357.92
   153.1 2357.06   170.3 2351.81     199 2348.32   208.9 2350.04   230.7 2348.89
   239.1 2351.97   265.7 2345.43   300.4 2341.54   309.1 2338.46   320.1 2331.81
  335.592327.316   349.4 2325.86  359.832327.319   374.7 2330.73     391 2331.97
   429.1 2329.09   496.8 2334.13   521.2 2338.43   545.6 2346.31   561.9 2348.75
     570 2348.28   606.6 2356.17     631 2358.65   651.3 2367.22   704.4 2383.19
#Mann= 6, -1 ,  0
       0     0.1       0      90    0.06       0   319.7     0.1       0
  335.59   0.045       0  359.83     0.1       0  538.85    0.08       0
#XS Ineff= 2 , 0
                          387.58         2348.17
Permanent Ineff=
       F       F
Bank Sta=335.59,359.83
XS Rating Curve= 0 ,0
Exp/Cntr=0.3,0.1

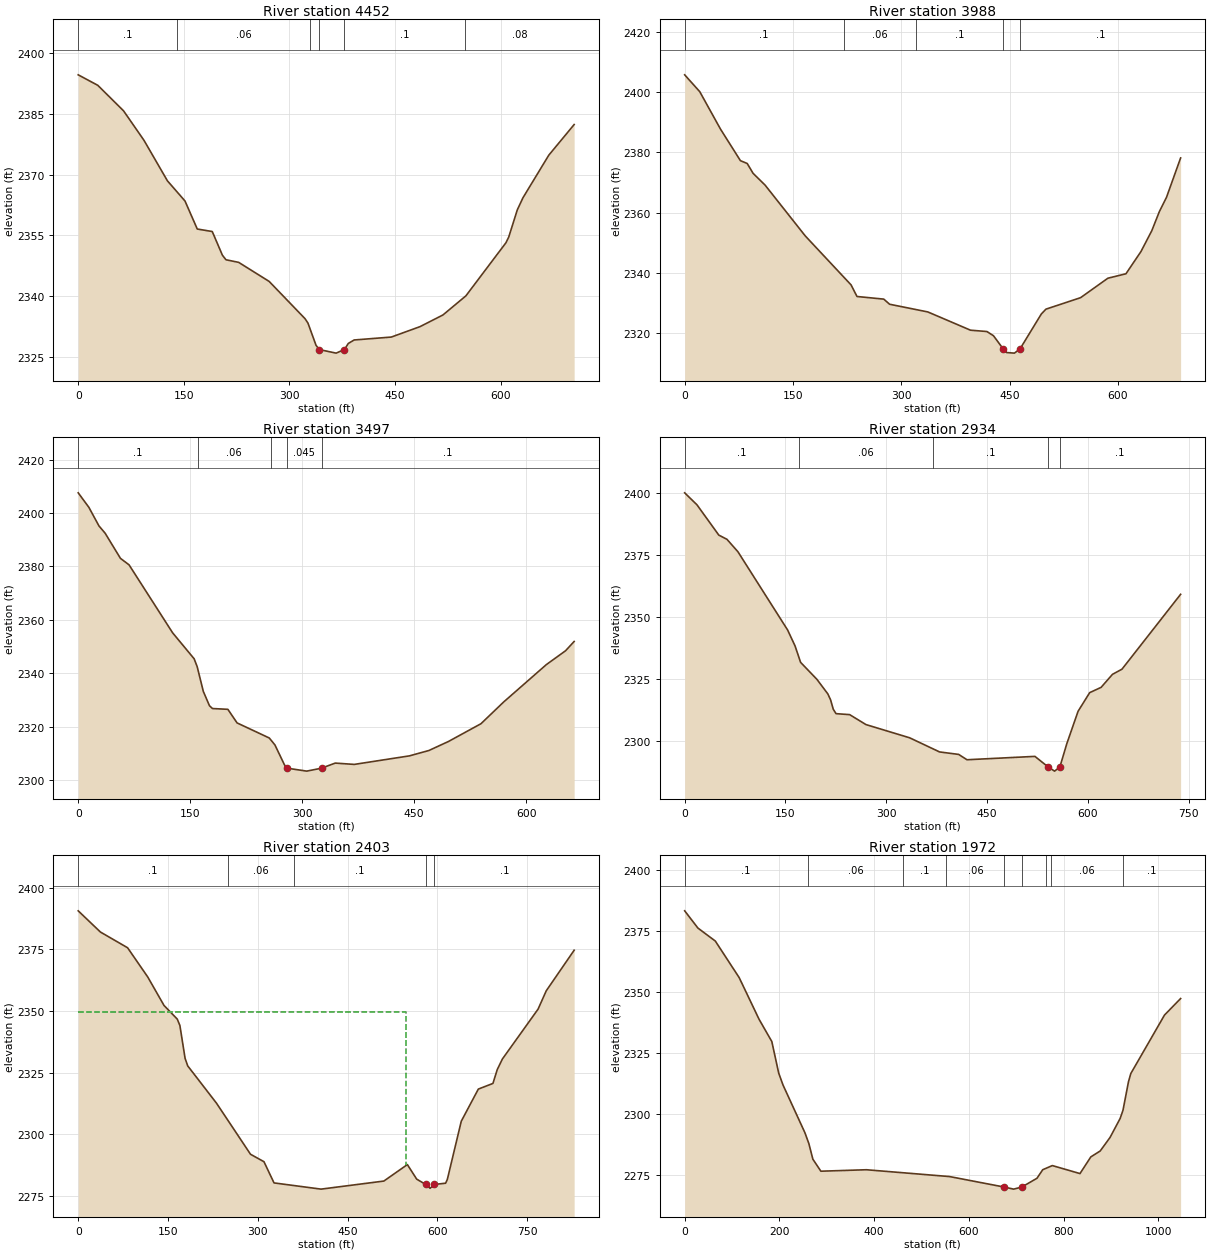
Type RM Length L Ch R = 1 ,4452    ,476.9,464.1,454.2
XS GIS Cut Line= 6
2263451.09533194685228.9074438362263648.18384967685093.614421571
2263711.83707945685123.6287569662263791.89483801685140.457808886
2263855.76909215685183.9026457092264087.59648031685225.713466655
#Sta/Elev= 30
       0 2394.66    27.8 2392.07    64.4 2385.76    93.5 2378.45   126.7 2368.46
   151.7 2363.46   169.1 2356.54   190.4 2355.92   204.8 2350.07   209.9 2348.94
   227.9  2348.3   271.2 2343.59   322.2 2334.37   326.3 2333.29   337.8 2327.79
  342.452326.741   366.3 2325.86  378.13 2326.74   383.6 2328.25   391.9 2329.11
   444.7 2329.83   485.5 2332.41     518 2335.29   550.6 2340.01   607.5 2353.14
   611.5 2354.56   623.7  2361.3   631.8  2364.3   668.4  2374.8   704.4 2382.37
#Mann= 6, -1 ,  0
       0     0.1       0     140    0.06       0   329.7     0.1       0
  342.45   0.045       0  378.13     0.1       0  548.85    0.08       0
Bank Sta=342.45,378.13
XS Rating Curve= 0 ,0
Exp/Cntr=0.3,0.1

Type RM Length L Ch R = 1 ,3988    ,472.4,490.7,499.2
XS GIS Cut Line= 4
2263519.87562739685677.7388248222263852.44134836685599.475831206
2264012.99266248 685513.465668762264114.32311661685385.939307419
#Sta/Elev= 30
       0 2405.64    20.9 2400.05    49.6 2387.65    77.2 2377.19    86.6 2376.25
    94.8 2372.97   111.3  2369.1     167 2352.24   230.4 2336.01   238.6 2332.17
   275.6  2331.3   283.8  2329.6   336.7 2327.05   395.8    2321   418.5 2320.56
   427.6 2319.16  440.922314.837   445.7 2313.59   456.6  2313.4  464.442314.837
   493.8 2326.36   500.2 2327.97   548.2 2331.78     586 2338.23     611  2339.7
   631.8 2347.07   646.8 2353.98   657.2 2360.27   667.2 2365.07   686.7 2378.09
#Mann= 5, -1 ,  0
       0     0.1       0     220    0.06       0     320     0.1       0
  440.92   0.045       0  464.44     0.1       0
Bank Sta=440.92,464.44
XS Rating Curve= 0 ,0
Exp/Cntr=0.3,0.1

Type RM Length L Ch R = 1 ,3497    ,582.6,563.2,527.9
XS GIS Cut Line= 4
2263681.08148102685973.6547549172263893.36128895 685923.51768769
2264036.99721027685974.9169203992264306.79889177685858.888614838
#Sta/Elev= 30
       0 2407.56    14.3 2402.12    27.8 2395.16    36.1 2392.42    56.6    2383
    68.1 2380.58   126.5  2355.1   155.3 2345.38   159.4  2342.4   167.6 2333.15
   175.8  2327.8   179.9 2326.73   200.5 2326.44   212.8 2321.35     256 2315.69
   263.6 2313.07   276.3 2305.64  279.932304.381   306.1 2303.28  325.992304.383
   344.3 2306.29   369.8  2305.8   443.8    2309   469.9 2311.02   496.1  2314.4
   539.6 2321.05   570.1 2329.22   627.1 2343.18   652.8 2348.36   664.4 2351.86
#Mann= 5, -1 ,  0
       0     0.1       0     160    0.06       0  258.12     0.1       0
  279.93   0.045       0  325.99     0.1       0
Bank Sta=279.93,325.99
XS Rating Curve= 0 ,0
Exp/Cntr=0.3,0.1

Type RM Length L Ch R = 1 ,2934    ,519.8,530.7,535.8
XS GIS Cut Line= 4
2263766.11846029686295.6127349842264178.33988725686226.178802404
2264312.94577329686157.1941364982264430.21952576686035.838725307
#Sta/Elev= 30
       0 2399.94    18.3 2395.11    50.8 2382.91    62.9 2381.22    79.2 2376.23
   153.2 2344.69   164.3 2338.25   172.5 2331.67   196.8 2324.82     213 2318.98
   217.1 2316.59   221.1 2312.81   225.2 2311.01   245.5 2310.61   269.8  2306.6
   334.7 2301.29   379.3 2295.59   407.7 2294.59   420.1 2292.44   521.2  2293.8
  541.132289.486   550.4 2287.86  558.262289.485   568.7 2298.96   585.4 2311.96
   602.7 2319.47   619.7  2321.6   636.6 2326.84   650.8 2328.93     738 2359.07
#Mann= 5, -1 ,  0
       0     0.1       0     170    0.06       0     370     0.1       0
  541.13   0.045       0  558.26     0.1       0
Bank Sta=541.13,558.26
XS Rating Curve= 0 ,0
Exp/Cntr=0.3,0.1

Type RM Length L Ch R = 1 ,2403    ,396.2,430.6,436.5
XS GIS Cut Line= 4
2263800.60104834 686403.811276022264305.42203029686625.465716084
2264411.95091264686693.7414699462264510.65611396686807.831017395
#Sta/Elev= 30
       0 2390.65    37.1 2382.05    82.5 2375.67   116.1 2363.85   143.4 2352.25
   165.5 2346.73   169.9 2344.14   178.6 2330.78     183 2327.74   231.1  2312.6
   287.9 2291.89   310.4 2288.86   327.2 2280.26   405.8 2277.74   510.7 2281.01
     550  2287.7   565.6 2281.79  580.76 2279.63   587.9 2278.09   595.3 2279.64
   613.9 2280.14   616.8 2281.68   640.1  2305.3   668.6 2318.33     693 2320.62
   700.3 2326.29   708.8 2330.53   768.4 2350.76   782.1 2358.21   828.7 2374.66
#Mann= 5, -1 ,  0
       0     0.1       0     250    0.06       0     360     0.1       0
  580.76   0.045       0   595.3     0.1       0
#XS Ineff= 2 , 0
          548.46 2349.61
Permanent Ineff=
       F       F
Bank Sta=580.76,595.3
XS Rating Curve= 0 ,0
Exp/Cntr=0.3,0.1

Type RM Length L Ch R = 1 ,1972    ,86.1,72.6,79.4
XS GIS Cut Line= 6
2263786.65992435686508.5480211052264108.10524901 686612.54384791
2264112.18886348 686854.10491685 2264063.5690491686960.409256761
2263970.00335523687059.284135518 2264124.9904414687204.438286336
#Sta/Elev= 30
       0 2383.07      28    2376    64.7 2370.69   115.1 2355.71   157.1 2338.64
     184 2329.53   198.6 2316.57   207.6 2311.74   253.8 2292.21   262.2 2287.75
   270.7 2281.33   287.6  2276.4   383.7    2277   559.6  2274.2  674.722269.908
   694.8 2269.06  711.882269.903     744 2273.52   756.1 2277.01   776.4 2278.71
   834.8 2275.43   857.7 2282.27   877.5 2284.69   898.3 2290.24   919.7 2298.05
   925.6 2301.37   937.2 2313.05   942.1  2316.4  1013.3 2340.38  1047.3 2347.14
#Mann= 9, -1 ,  0
       0     0.1       0     260    0.06       0  461.01     0.1       0
  552.81    0.06       0  674.72   0.045       0  711.88    0.06       0
  763.82     0.1       0  773.82    0.06       0     925     0.1       0
Bank Sta=674.72,711.88
XS Rating Curve= 0 ,0
Exp/Cntr=0.3,0.1

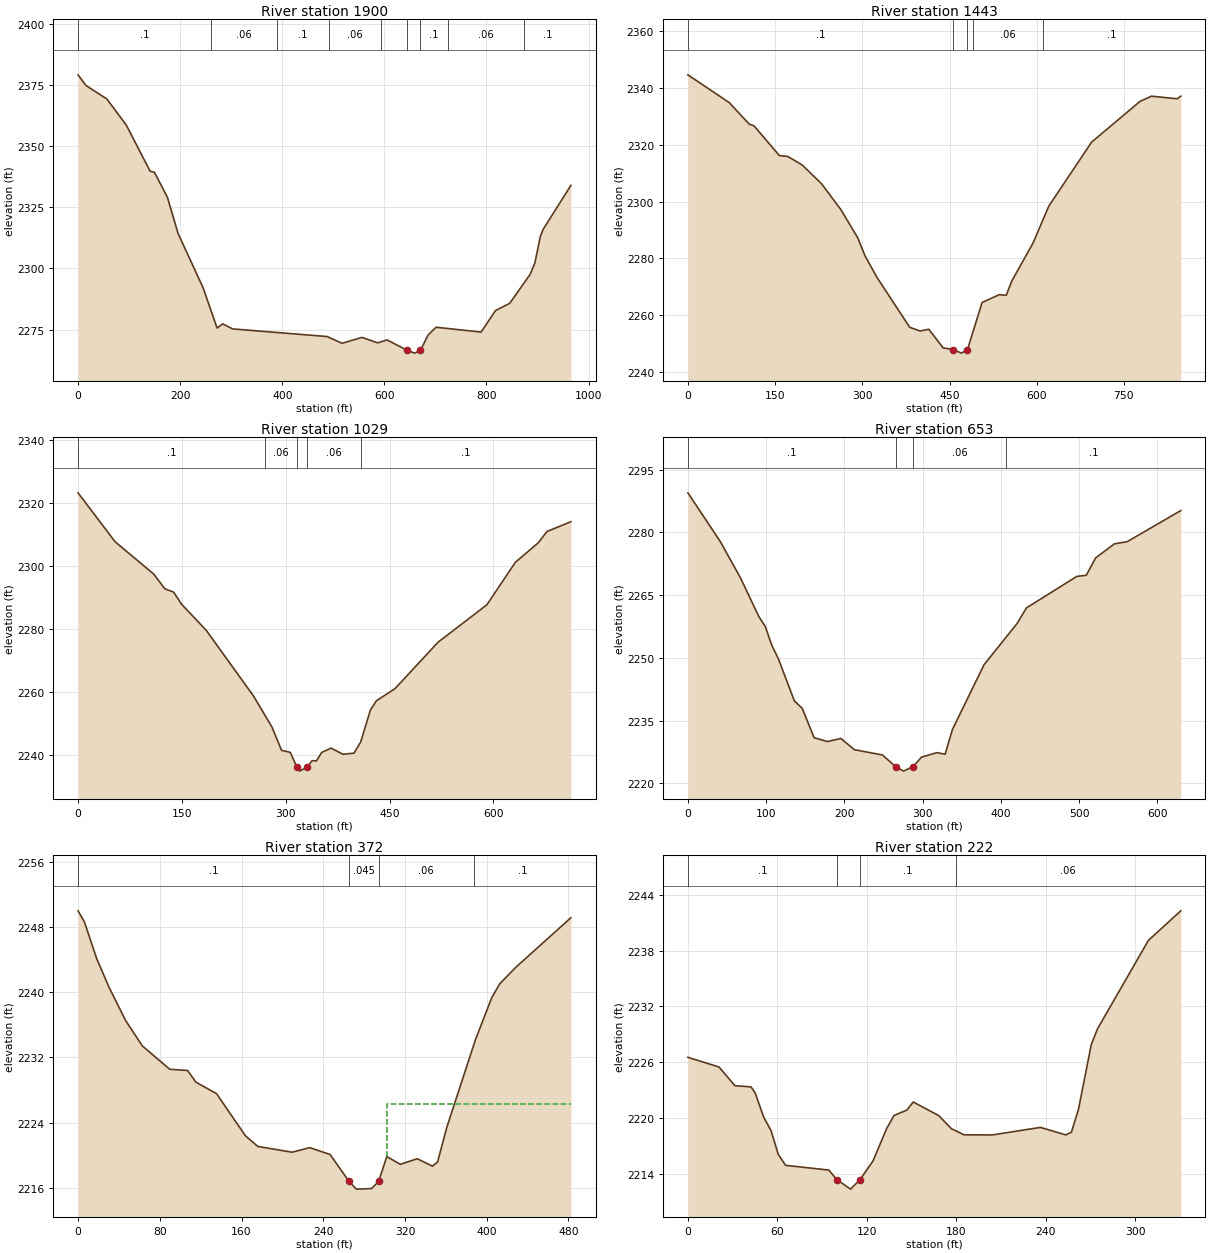
Type RM Length L Ch R = 1 ,1900    ,468.7,456.7,433.2
XS GIS Cut Line= 6
2263786.84162667686526.832676725 2264051.4288983686618.497841427
2264058.93769669686836.0826229442264010.31788231686942.386962856
2263916.75218845687041.2618416122264071.73927461 687186.41599243
#Sta/Elev= 30
       0 2379.06    15.5 2374.71    56.4  2369.2    94.5 2358.54   141.1 2339.72
   149.6 2339.26     175 2329.05   196.1 2314.17     245 2292.05   272.3 2275.65
   283.3 2277.36   302.7 2275.28   487.8 2272.17   517.2  2269.4     556 2271.82
     587 2269.58   605.3 2270.79     645  2266.5   659.3 2265.39   670.7 2266.49
   685.7 2272.79   701.2 2275.96   789.5 2273.99   817.8 2282.78   845.6 2285.74
   885.7  2297.6   894.9 2302.27   905.5    2313   911.3 2316.04   965.5 2333.93
#Mann= 9, -1 ,  0
       0     0.1       0     260    0.06       0   389.2     0.1       0
  491.01    0.06       0  593.43     0.1       0     645   0.045       0
   670.7     0.1       0  724.73    0.06       0  873.19     0.1       0
Bank Sta=645,670.7
XS Rating Curve= 0 ,0
Exp/Cntr=0.3,0.1

Type RM Length L Ch R = 1 ,1443    ,413.4,413.9,413.8
XS GIS Cut Line= 4
2263542.53219473686775.519380588 2263637.6692701687122.373301187
2263778.39286074687251.2047574092264038.03779559687395.892392859
#Sta/Elev= 30
       0 2344.69      71 2334.91   105.4 2327.32   113.7  2326.7   157.4  2316.2
   171.8  2315.9   196.7 2312.86   229.8 2306.29   263.1 2297.14   292.1 2287.22
   304.5  2280.9   325.2 2273.22   381.6 2255.61   399.4 2254.32   414.4 2254.93
     439 2248.36  456.692247.749   470.4 2246.51  480.852247.749     506 2264.37
   535.6 2267.14   547.5 2266.91   557.1 2271.96   593.7 2285.38   620.8  2298.4
   694.4 2320.96   777.5  2335.3   797.3 2337.16   841.4 2336.24   847.7 2337.16
#Mann= 5, -1 ,  0
       0     0.1       0  456.69   0.045       0  480.85     0.1       0
  489.66    0.06       0  610.45     0.1       0
Bank Sta=456.69,480.85
XS Rating Curve= 0 ,0
Exp/Cntr(USF)=0,0
Exp/Cntr=0.3,0.1

Type RM Length L Ch R = 1 ,1029    ,377.3,376.2,375.4
XS GIS Cut Line= 4
2263272.09624902687168.180041177  2263375.161414687437.735088042
2263498.04680301687538.8182306162263753.72769305687606.206992333
#Sta/Elev= 30
       0  2323.2    53.5 2307.66   109.3 2297.39   125.3 2292.72   138.1 2291.64
   149.5 2287.82   185.2 2279.51   253.7 2258.56   280.2 2248.76     294 2241.37
   306.6 2240.73  316.082236.078   320.2 2234.76  331.132236.076   338.1 2238.08
   344.4    2238   352.1 2240.71   365.6 2242.08   382.7 2240.12   398.7 2240.47
   408.3 2244.01   422.5 2254.24     431 2257.11   457.9 2260.97   520.2 2275.75
   590.6 2287.61   631.9 2301.14     665 2307.34   677.4  2310.9   712.1 2314.03
#Mann= 5, -1 ,  0
       0     0.1       0     270    0.06       0  316.08   0.045       0
  331.13    0.06       0  408.59     0.1       0
Bank Sta=316.08,331.13
XS Rating Curve= 0 ,0
Exp/Cntr(USF)=0,0
Exp/Cntr=0.3,0.1

Type RM Length L Ch R = 1 ,653     ,281.1,280.9,280.5
XS GIS Cut Line= 4
2262994.61311254687493.2317153382263032.27153821687641.883395594
2263218.58164413687782.6069862372263460.38837735687806.391255078
#Sta/Elev= 30
       0 2289.49    41.2  2277.9    67.1 2269.19    90.7 2259.88      99 2257.49
   107.2 2253.02   115.5 2249.85   136.1 2239.69   146.1 2237.94   161.3  2230.9
   178.3 2229.99   195.6 2230.72   212.7 2228.04   248.5 2226.78  265.552223.977
   275.6 2222.91  287.732223.979   298.6 2226.26   318.1 2227.33   328.7 2226.96
     338 2232.86   378.4 2248.36   420.6 2258.21   432.6 2261.96     497  2269.5
     509 2269.76   521.1 2273.94   545.2  2277.3   561.3  2277.8   629.8 2285.24
#Mann= 4, -1 ,  0
       0     0.1       0  265.55   0.045       0  287.73    0.06       0
  406.83     0.1       0
Bank Sta=265.55,287.73
XS Rating Curve= 0 ,0
Exp/Cntr(USF)=0,0
Exp/Cntr=0.3,0.1

Type RM Length L Ch R = 1 ,372     ,152.5,150.3,148.6
XS GIS Cut Line= 4
2262852.87301279687687.0432532442262880.00900876687877.869839619
2263012.44433287687975.3651853432263137.66168565687973.132330999
#Sta/Elev= 30
       0 2249.99     6.2 2248.64    18.3 2244.11    30.4 2240.59    46.6 2236.52
    62.8 2233.43    89.7 2230.55   107.2  2230.4   115.3 2228.97   135.5 2227.56
   163.8 2222.39   175.9 2221.08   209.5 2220.37   226.7 2220.93   246.7 2220.09
  265.162216.795   272.4 2215.84   287.3 2215.91   294.22216.795   302.2 2219.84
   315.4 2218.88     332 2219.57   346.8 2218.66   351.9 2219.18   360.9 2223.42
   388.9 2234.16   404.9 2239.34   412.9 2241.06     428 2243.01   482.4 2249.15
#Mann= 4, -1 ,  0
       0     0.1       0  265.16   0.045       0   294.2    0.06       0
   387.2     0.1       0
#XS Ineff= 2 , 0
                          302.78         2226.29
Permanent Ineff=
       F       F
Bank Sta=265.16,294.2
XS Rating Curve= 0 ,0
Exp/Cntr(USF)=0,0
Exp/Cntr=0.3,0.1

Type RM Length L Ch R = 1 ,222     ,53.2,53.9,53.1
XS GIS Cut Line= 4
2262798.19600042687985.6006503572262831.51810406 688023.05115622
2262905.23957229688073.4766404932263084.53018304688007.422204954
#Sta/Elev= 30
       0 2226.53    20.9 2225.48    31.6 2223.47    42.3 2223.35    45.1  2222.7
    50.9 2220.07    55.8 2218.63    60.6 2216.09    65.5 2214.91    94.5  2214.4
   99.88 2213.37   109.1 2212.35   115.4 2213.37   124.1 2215.37   133.3 2218.87
   138.2 2220.27   146.8 2220.85   151.1 2221.72   168.2 2220.26   176.7 2218.85
   185.2 2218.19   204.3 2218.18   236.4 2218.99   253.4 2218.18   257.2 2218.48
   261.9 2220.93   270.5  2227.9   274.7  2229.6   308.8  2239.1   330.5 2242.28
#Mann= 4, -1 ,  0
       0     0.1       0   99.88   0.045       0   115.4     0.1       0
  179.45    0.06       0
Bank Sta=99.88,115.4
XS Rating Curve= 0 ,0
Exp/Cntr(USF)=0,0
Exp/Cntr=0.3,0.1

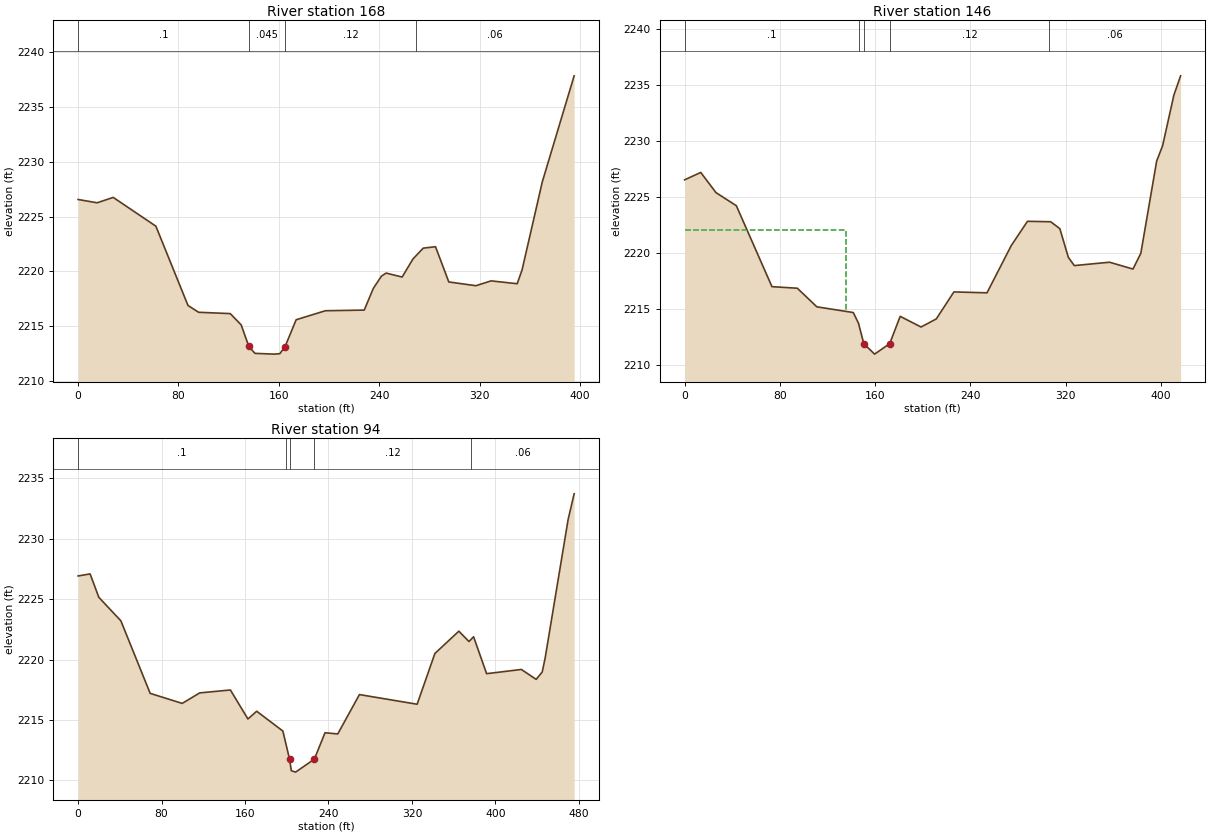
Type RM Length L Ch R = 1 ,168     ,22.8,22.3,20.2
XS GIS Cut Line= 5
2262786.10567963 687990.908596072262820.31244089688084.387417791
2262910.25263214688124.1970106382262931.18952911688130.094728097
2263073.91429162688027.474444314
#Sta/Elev= 30
       0 2226.55    15.2 2226.25      28 2226.74      62 2224.12    87.6  2216.9
    96.1 2216.28   121.3 2216.16     130 2215.13  136.09 2213.17     141 2212.54
   156.3 2212.47   160.8 2212.51     165 2213.16   173.8  2215.6   197.1 2216.42
   228.1 2216.48   235.3 2218.45   241.8 2219.57   245.5 2219.85   258.3 2219.49
   266.9 2221.13   275.1 2222.12   284.9 2222.25   295.5 2219.04   317.1  2218.7
   329.2 2219.14     350 2218.88   353.9 2220.14     370 2228.15   395.4 2237.81
#Mann= 4, -1 ,  0
       0     0.1       0  136.09   0.045       0     165    0.12       0
  269.65    0.06       0
Bank Sta=136.09,165
XS Rating Curve= 0 ,0
Exp/Cntr(USF)=0,0
Exp/Cntr=0.3,0.1

Type RM Length L Ch R = 1 ,146     ,55.7,51.2,43.4
XS GIS Cut Line= 5
2262778.43864693688004.4733462252262815.59426692688103.849885406
2262905.53445817688143.6594782522262926.47135515688149.557195711
2263080.40178082688037.500563994
#Sta/Elev= 30
       0  2226.5    13.6 2227.16    26.4 2225.36    43.5 2224.19    73.4 2216.97
    94.7 2216.83   111.1 2215.17   141.7 2214.66   146.1  2213.7   150.5 2211.89
   159.6 2210.95   172.3 2211.89   181.1 2214.32   198.6 2213.37   211.4 2214.09
   226.2  2216.5     254 2216.42   274.4 2220.64     288  2222.8   307.5 2222.76
   315.2 2222.14   322.3 2219.59   327.3 2218.85   356.9 2219.15   376.6 2218.54
   383.2 2219.95   396.5 2228.18   401.5 2229.55   410.9 2234.04   416.6 2235.78
#Mann= 5, -1 ,  0
       0     0.1       0   146.1    0.12       0   150.5   0.045       0
   172.3    0.12       0   306.2    0.06       0
#XS Ineff= 2 , 0
          135.69 2222.01
Permanent Ineff=
       F       F
Bank Sta=150.5,172.3
XS Rating Curve= 0 ,0
Exp/Cntr(USF)=0,0
Exp/Cntr=0.3,0.1

Type RM Length L Ch R = 1 ,94      ,,,
XS GIS Cut Line= 4
 2262776.1621278688010.1938706172262831.13552513688180.676160914
2262917.57014353688168.2982932952263084.78722246688042.847037628
#Sta/Elev= 30
       0 2226.93    11.5  2227.1    19.9 2225.16      41 2223.22    69.1 2217.21
    99.8 2216.38   116.6 2217.25     146 2217.49   162.8 2215.09   171.2 2215.73
   196.3 2214.09  202.68 2211.77   204.4 2210.81   208.5 2210.69  226.492211.768
   236.7 2213.95   248.9 2213.85   269.7 2217.11     325 2216.31     342 2220.51
     365 2222.36   374.7  2221.5   379.1  2221.9   391.6 2218.84   424.9 2219.19
   439.1 2218.37   444.9 2218.98   447.7 2220.13   469.7 2231.59   475.5 2233.73
#Mann= 5, -1 ,  0
       0     0.1       0  199.13    0.12       0  202.68   0.045       0
  226.49    0.12       0  376.44    0.06       0
Bank Sta=202.68,226.49
XS Rating Curve= 0 ,0
Exp/Cntr(USF)=0,0
Exp/Cntr=0.3,0.1
LCMann Table=0

Chan Stop Cuts=-1
Use User Specified Reach Order=0
Composite Channel Slope=5